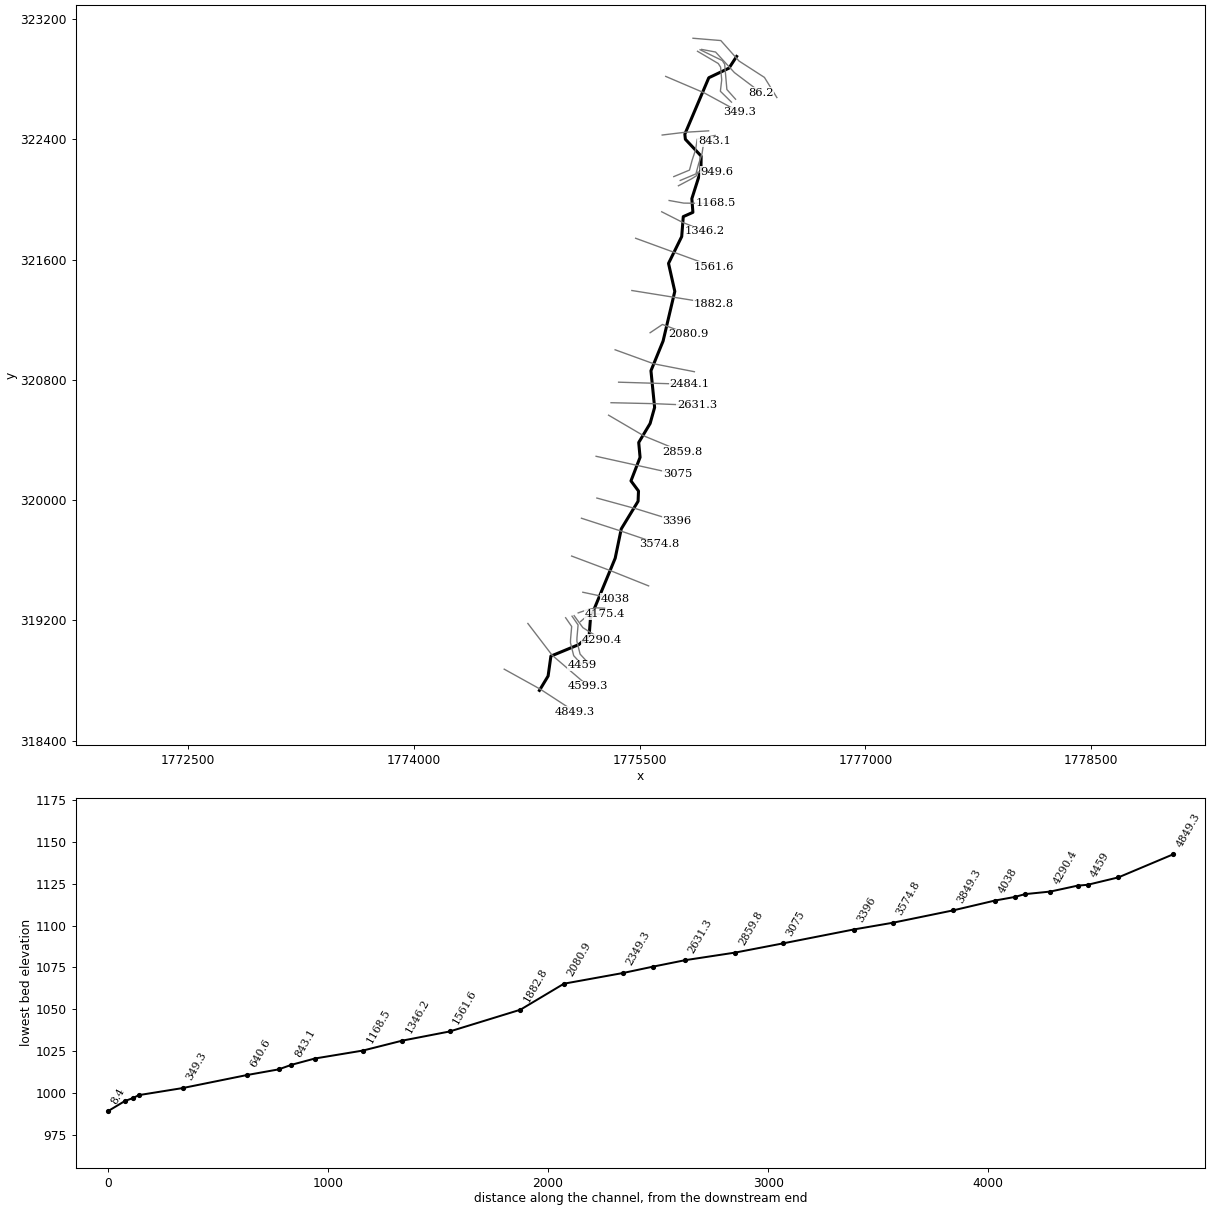
--- GRAPEVINBR.prj (project) ---

Proj Title=GRAPEVINBR
Current Plan=p01
Geom File=g01
Flow File=f01
Plan File=p01
DSS Export Rating Curves=0
DSS Export Rating Curve Sorted=0
DSS Export Volume Flow Curves=0
DXF OffsetX=0
DXF OffsetY=0
DXF ScaleX=0
DXF ScaleY=0

--- GRAPEVINBR.p01 (plan) ---

Plan Title=Floodplain
Program Version=4.00
Geom File=g01
Flow File=f01
K Sum by GR=0
Std Step Tol=0.01
Critical Tol=0.01
Num of Std Step Trials=20
Max Error Tol=0.3
Flow Tol Ratio=0.001
Split Flow NTrial=30
Split Flow Tol=0.02
Split Flow Ratio=0.02
Log Output Level=0
Friction Slope Method=1
Unsteady Friction Slope Method=2
Unsteady Bridges Friction Slope Method=1
Global Log Level=0
CheckData=False
Run HTab=0
Run UNet=0
Run PostProcess=0
UNET Theta=0
UNET Theta Warmup=0
UNET ZTol=0
UNET ZSATol=0
UNET MxIter=0
UNET MaxInSteps=0
UNET DtIC=0
UNET DtMin=0
UNET MaxCRTS=0
UNET WFStab=0
UNET SFStab=0
UNET WFX=0
UNET SFX=0
UNET DSS MLevel=0
UNET DZMax Abort=0
UNET Convert EG Bridges=0
UNET Use Existing IB Tables=0
UNET Froude Limit=0
UNET Froude Power=0
Write IC File=0
Echo Input=False
Echo Output=False
Write Detailed=0

--- GRAPEVINBR.f01 (steady flow) ---

Flow Title=NFF Regression Equation
Program Version=4.00
Number of Profiles=1
Profile Names=P100yr
River Rch & RM=GRAPEVINBR,Main      ,4849.3
881.8345
River Rch & RM=GRAPEVINBR,Main      ,4175.4
903.5946
River Rch & RM=GRAPEVINBR,Main      ,2349.3
958.8397
River Rch & RM=GRAPEVINBR,Main      ,150.3
1003.489
Boundary for River Rch & Prof#=GRAPEVINBR,Main      ,1
Up Type=0
Dn Type=3
Dn Slope=0.060701

--- GRAPEVINBR.g01 (geometry) ---

Geom Title=USGS 10m DEM_Batch
Program Version=4.00

River Reach=GRAPEVINBR     ,Main
Reach XY= 30
     1774835.312      318734.153     1774892.819      318829.696
     1774911.384      318962.188     1775097.228      319039.253
     1775165.283      319098.281     1775174.311      319216.337
     1775338.200      319613.073     1775378.477      319808.211
     1775490.283      319992.239     1775493.061      320060.295
     1775443.061      320127.656     1775503.478      320284.323
     1775494.450      320382.934     1775570.144      320509.323
     1775600.005      320616.267     1775575.700      320860.156
     1775656.255      321057.517     1775734.033      321388.003
     1775692.367      321574.114     1775779.866      321752.517
     1775790.283      321885.156     1775854.172      321913.628
     1775847.228      322004.600     1775907.644      322194.809
     1775909.033      322287.934     1775804.172      322399.739
     1775800.700      322433.767     1775959.728      322808.767
     1776093.755      322872.656     1776144.450      322950.434

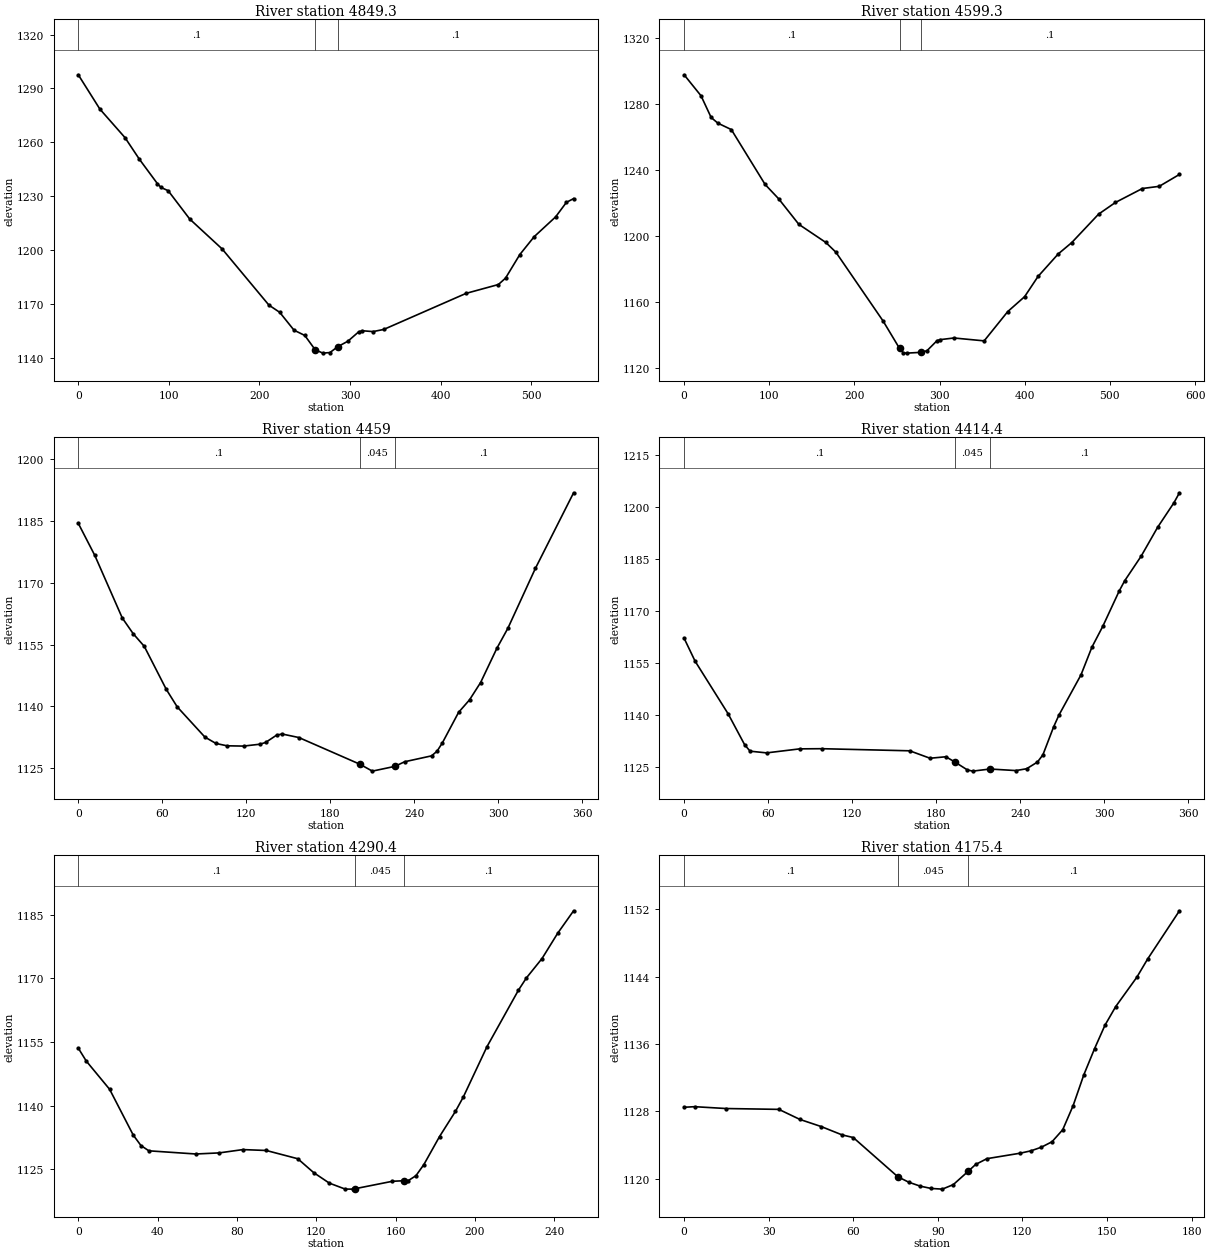
Type RM Length L Ch R = 1 ,4849.3,261.3,250,246
XS GIS Cut Line= 3
     1774601.346      318875.441     1774840.779      318742.527
     1775069.257      318593.381
#Sta/Elev= 30
       0 1297.59    23.8 1278.51    51.6 1262.57    67.5 1250.51    87.3 1236.99
    91.3 1234.85    99.2 1233.04   123.0 1217.25   158.8 1200.58   210.4 1169.31
   222.3 1165.30   238.1 1155.35   250.0 1152.41   261.4 1144.49   269.9 1142.56
   277.8 1142.88   286.4 1146.16   297.6 1149.20   309.4 1154.38   313.4 1155.03
   325.3 1154.56   337.1 1155.74   428.1 1175.86   463.7 1180.77   471.6 1184.34
   487.4 1197.49   503.2 1207.42   526.9 1218.46   538.8 1226.55   546.7 1228.63
#Mann= 3 , 0 , 0
       0     0.1       0   261.4   0.045       0   286.4     0.1       0
Bank Sta=261.4,286.4
Exp/Cntr=0.3,0.1

Type RM Length L Ch R = 1 ,4599.3,151.6,140.3,123.1
XS GIS Cut Line= 3
     1774758.475      319179.325     1774919.536      318968.412
     1775159.360      318762.337
#Sta/Elev= 30
       0 1297.44    19.8 1284.75    31.7 1271.58    39.6 1268.14    55.4 1264.25
    95.1 1230.96   110.9 1222.34   134.7 1206.80   166.4 1195.81   178.2 1189.91
   233.7 1148.14   252.9 1131.62   257.4 1128.86   261.4 1128.74   277.9 1129.21
   285.1 1130.17   297.0 1136.32   301.0 1136.93   316.8 1137.92   352.3 1136.17
   380.0 1153.93   399.8 1162.96   415.6 1175.24   439.3 1188.88   455.1 1195.71
   486.7 1213.00   506.5 1220.08   538.1 1228.53   557.9 1229.85   581.6 1237.05
#Mann= 3 , 0 , 0
       0     0.1       0   252.9   0.045       0   277.9     0.1       0
Bank Sta=252.9,277.9
Exp/Cntr=0.3,0.1

Type RM Length L Ch R = 1 ,4459,46.4,44.6,44.9
XS GIS Cut Line= 6
     1775009.189      319217.482     1775049.340      319159.379
     1775041.828      319072.864     1775041.307      319051.163
     1775062.661      318965.226     1775120.821      318901.857
#Sta/Elev= 30
       0 1184.46    11.8 1176.67    31.4 1161.49    39.2 1157.67    47.1 1154.61
    62.8 1144.17    70.6 1139.92    90.4 1132.57    98.3 1131.02   106.2 1130.45
   118.0 1130.38   129.8 1130.84   133.8 1131.27   141.7 1133.06   145.6 1133.31
   157.5 1132.46     201 1125.99   210.0 1124.30     226 1125.45   233.1 1126.58
   252.3 1128.01   256.2 1129.14   260.0 1131.16   271.6 1138.58   279.4 1141.61
   287.3 1145.81   299.0 1154.18   306.8 1159.00   326.4 1173.51   353.7 1191.88
#Mann= 3 , 0 , 0
       0     0.1       0     201   0.045       0     226     0.1       0
Bank Sta=201,226
Exp/Cntr=0.3,0.1

Type RM Length L Ch R = 1 ,4414.4,103.1,123.9,144.2
XS GIS Cut Line= 6
     1775051.723      319227.899     1775091.875      319169.796
     1775084.362      319083.281     1775083.841      319061.580
     1775105.196      318975.642     1775163.355      318912.274
#Sta/Elev= 30
       0 1162.18     7.8 1155.59    31.4 1140.38    43.2 1131.44    47.1 1129.58
    58.9 1129.09    82.5 1130.25    98.3 1130.30   161.1 1129.69   175.6 1127.54
   186.9 1127.97   193.4 1126.44   202.3 1124.16   206.1 1123.82   218.4 1124.43
   236.9 1123.98   244.6 1124.51   252.3 1126.44   256.2 1128.52   263.9 1136.64
   267.7 1140.04   283.4 1151.62   291.2 1159.62   299.0 1165.67   310.7 1175.86
   314.6 1178.80   326.4 1185.93   338.1 1194.23   349.8 1201.35   353.7 1204.21
#Mann= 3 , 0 , 0
       0     0.1       0   193.4   0.045       0   218.4     0.1       0
Bank Sta=193.4,218.4
Exp/Cntr=0.3,0.1

Type RM Length L Ch R = 1 ,4290.4,87.6,115.1,138.9
XS GIS Cut Line= 3
     1775065.612      319231.371     1775123.772      319151.510
     1775251.376      319070.781
#Sta/Elev= 30
       0 1153.55     4.0 1150.52    15.8 1143.84    27.7 1133.05    31.6 1130.57
    35.6 1129.33    59.3 1128.58    71.1 1128.84    83.0 1129.62    94.8 1129.41
   110.7 1127.46   118.7 1124.19   126.6 1121.71   134.6 1120.30   138.5 1120.29
   139.5 1120.38   158.4 1122.14   164.5 1122.28   166.4 1122.29   170.3 1123.46
   174.3 1126.09   182.2 1132.70   190.2 1138.62   194.2 1142.04   206.1 1153.88
   222.0 1167.24   226.0 1170.12   233.9 1174.71   241.8 1180.68   249.8 1185.96
#Mann= 3 , 0 , 0
       0     0.1       0   139.5   0.045       0   164.5     0.1       0
Bank Sta=139.5,164.5
Exp/Cntr=0.3,0.1

Type RM Length L Ch R = 1 ,4175.4,49.3,47.9,42.9
XS GIS Cut Line= 4
     1775108.147      319192.309     1775150.682      319228.767
     1775212.314      319242.656     1775268.737      319240.052
#Sta/Elev= 30
       0 1128.48     3.7 1128.55    14.9 1128.33    33.6 1128.23    41.1 1127.03
    48.6 1126.19    56.0 1125.20    60.0 1124.88    75.8 1120.22    79.7 1119.57
    83.7 1119.11    87.6 1118.83    91.6 1118.75    95.5 1119.29   100.8 1120.88
   103.4 1121.68   107.4 1122.37   119.2 1123.02   123.0 1123.30   126.7 1123.73
   130.5 1124.38   134.3 1125.81   138.0 1128.68   141.8 1132.35   145.6 1135.45
   149.3 1138.24   153.1 1140.45   160.6 1143.94   164.4 1146.09   175.7 1151.83
#Mann= 3 , 0 , 0
       0     0.1       0    75.8   0.045       0   100.8     0.1       0
Bank Sta=75.8,100.8
Exp/Cntr=0.3,0.1

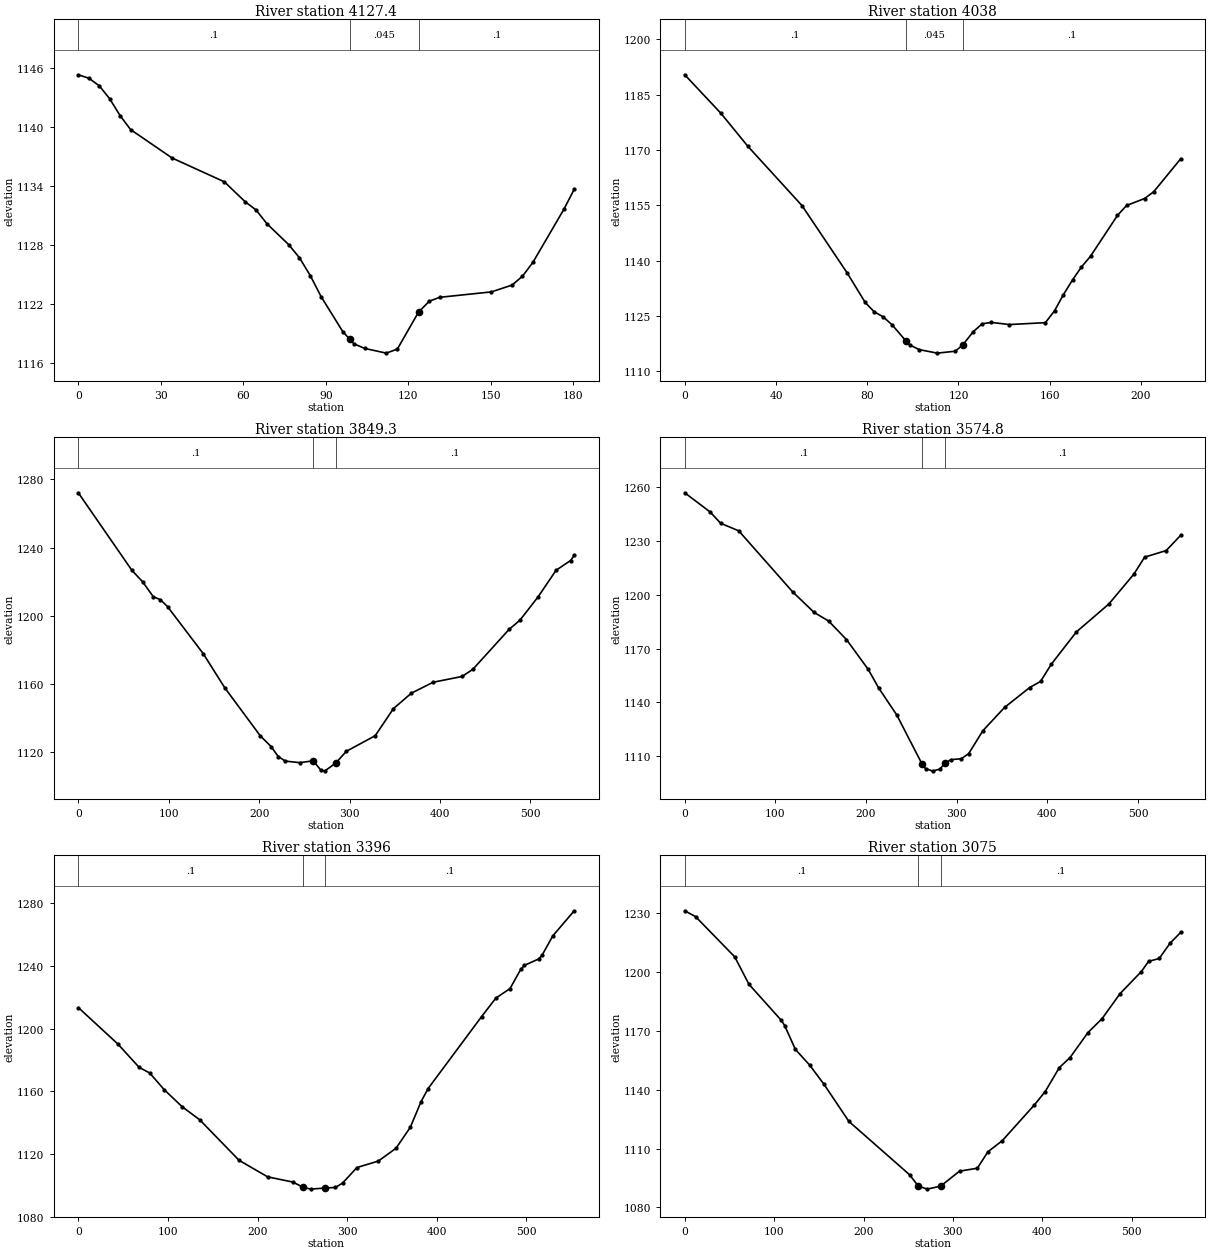
Type RM Length L Ch R = 1 ,4127.4,103.4,89.4,81
XS GIS Cut Line= 4
     1775092.522      319249.601     1775149.814      319269.566
     1775211.446      319283.455     1775267.869      319280.851
#Sta/Elev= 30
       0 1145.30     3.8 1144.96     7.6 1144.19    11.4 1142.87    15.2 1141.15
    19.0 1139.74    34.1 1136.85    53.1 1134.43    60.7 1132.40    64.6 1131.58
    68.6 1130.17    76.5 1128.05    80.4 1126.72    84.4 1124.88    88.3 1122.76
    96.2 1119.20    98.7 1118.44   100.2 1117.98   104.1 1117.51   112.0 1117.03
   116.0 1117.44   123.7 1121.19   127.6 1122.30   131.4 1122.70   150.2 1123.25
   157.7 1123.94   161.5 1124.84   165.3 1126.25   176.6 1131.66   180.3 1133.66
#Mann= 3 , 0 , 0
       0     0.1       0    98.7   0.045       0   123.7     0.1       0
Bank Sta=98.7,123.7
Exp/Cntr=0.3,0.1

Type RM Length L Ch R = 1 ,4038,192.7,188.7,184.1
XS GIS Cut Line= 2
     1775123.251      319387.101     1775335.925      319341.962
#Sta/Elev= 30
       0 1190.37    15.8 1179.96    27.7 1170.96    51.4 1154.90    71.2 1136.65
    79.1 1128.65    83.0 1126.14    87.0 1124.74    90.9 1122.58    96.8 1118.33
    98.8 1117.08   102.8 1115.86   110.7 1114.91   118.6 1115.43   121.8 1117.08
   126.5 1120.74   130.4 1122.87   134.4 1123.24   142.3 1122.66   158.1 1123.17
   162.1 1126.37   166.0 1130.75   170.0 1134.76   173.9 1138.25   177.9 1141.19
   189.7 1152.25   193.7 1154.94   201.6 1156.83   205.6 1158.67   217.4 1167.58
#Mann= 3 , 0 , 0
       0     0.1       0    96.8   0.045       0   121.8     0.1       0
Bank Sta=96.8,121.8
Exp/Cntr=0.3,0.1

Type RM Length L Ch R = 1 ,3849.3,273,274.4,275.8
XS GIS Cut Line= 3
     1775049.069      319627.713     1775303.989      319531.768
     1775560.227      319429.263
#Sta/Elev= 30
       0 1272.14    59.2 1226.77    71.1 1220.01    82.9 1211.28    90.8 1209.50
    98.7 1205.45   138.2 1177.87   161.8 1158.04   201.3 1129.72   213.2 1123.50
   221.1 1117.62   229.0 1114.95   244.8 1114.05   259.9 1115.11   268.4 1109.54
   272.4 1109.08   284.9 1113.90   296.4 1120.69   328.4 1129.85   348.4 1145.64
   368.4 1154.78   392.4 1161.15   424.4 1164.54   436.4 1168.75   476.4 1192.11
   488.4 1197.50   508.4 1211.10   528.4 1226.76   544.4 1232.46   548.4 1235.46
#Mann= 3 , 0 , 0
       0     0.1       0   259.9   0.045       0   284.9     0.1       0
Bank Sta=259.9,284.9
Exp/Cntr=0.3,0.1

Type RM Length L Ch R = 1 ,3574.8,177.4,178.8,179.7
XS GIS Cut Line= 3
     1775114.323      319879.219     1775374.441      319794.602
     1775633.378      319706.443
#Sta/Elev= 30
       0 1256.84    27.8 1246.23    39.6 1239.86    59.5 1235.66   118.9 1201.69
   142.7 1190.15   158.6 1185.42   178.4 1175.03   202.2 1158.55   214.1 1147.91
   233.9 1132.99   261.8 1105.63   265.6 1103.15   273.5 1101.69   281.5 1102.86
   286.8 1105.96   293.4 1108.06   305.2 1108.62   313.2 1111.43   329.0 1124.27
   352.8 1137.18   380.6 1148.31   392.5 1151.68   404.4 1161.29   432.1 1179.30
   467.8 1194.81   495.5 1211.49   507.4 1220.99   531.2 1224.65   547.1 1233.14
#Mann= 3 , 0 , 0
       0     0.1       0   261.8   0.045       0   286.8     0.1       0
Bank Sta=261.8,286.8
Exp/Cntr=0.3,0.1

Type RM Length L Ch R = 1 ,3396,318.6,321,324
XS GIS Cut Line= 3
     1775216.610      320013.524     1775478.112      319941.910
     1775747.853      319858.678
#Sta/Elev= 30
       0 1213.42    43.9 1190.29    67.8 1175.34    79.7 1171.66    95.7 1161.15
   115.6 1150.32   135.6 1141.79   179.4 1116.03   211.3 1105.47   239.2 1102.19
   250.6 1098.93   259.2 1097.65   275.6 1098.35   287.0 1098.72   295.0 1101.53
   310.9 1111.41   334.8 1115.53   354.6 1123.72   370.5 1137.07   382.5 1153.41
   390.4 1161.79   450.0 1207.59   466.0 1219.45   481.8 1225.50   493.8 1237.78
   497.8 1240.27   513.7 1244.39   517.6 1246.81   529.6 1259.13   553.4 1275.09
#Mann= 3 , 0 , 0
       0     0.1       0   250.6   0.045       0   275.6     0.1       0
Bank Sta=250.6,275.6
Exp/Cntr=0.3,0.1

Type RM Length L Ch R = 1 ,3075,223.8,215.2,209.1
XS GIS Cut Line= 2
     1775211.497      320291.220     1775753.162      320171.056
#Sta/Elev= 30
       0 1231.35    12.0 1228.42    55.9 1207.84    71.8 1193.87   107.8 1175.57
   111.8 1172.80   123.7 1160.67   139.7 1152.64   155.7 1142.89   183.6 1123.91
   251.5 1096.70   261.3 1090.91   271.4 1089.36   286.3 1090.90   307.4 1098.53
   327.3 1100.02   339.3 1108.47   355.2 1114.06   391.2 1132.34   403.2 1139.09
   419.1 1151.37   431.1 1156.50   451.0 1169.17   467.0 1176.39   487.0 1189.10
   510.9 1200.38   518.9 1205.55   530.9 1207.04   542.9 1214.77   554.8 1220.31
#Mann= 3 , 0 , 0
       0     0.1       0   261.3   0.045       0   286.3     0.1       0
Bank Sta=261.3,286.3
Exp/Cntr=0.3,0.1

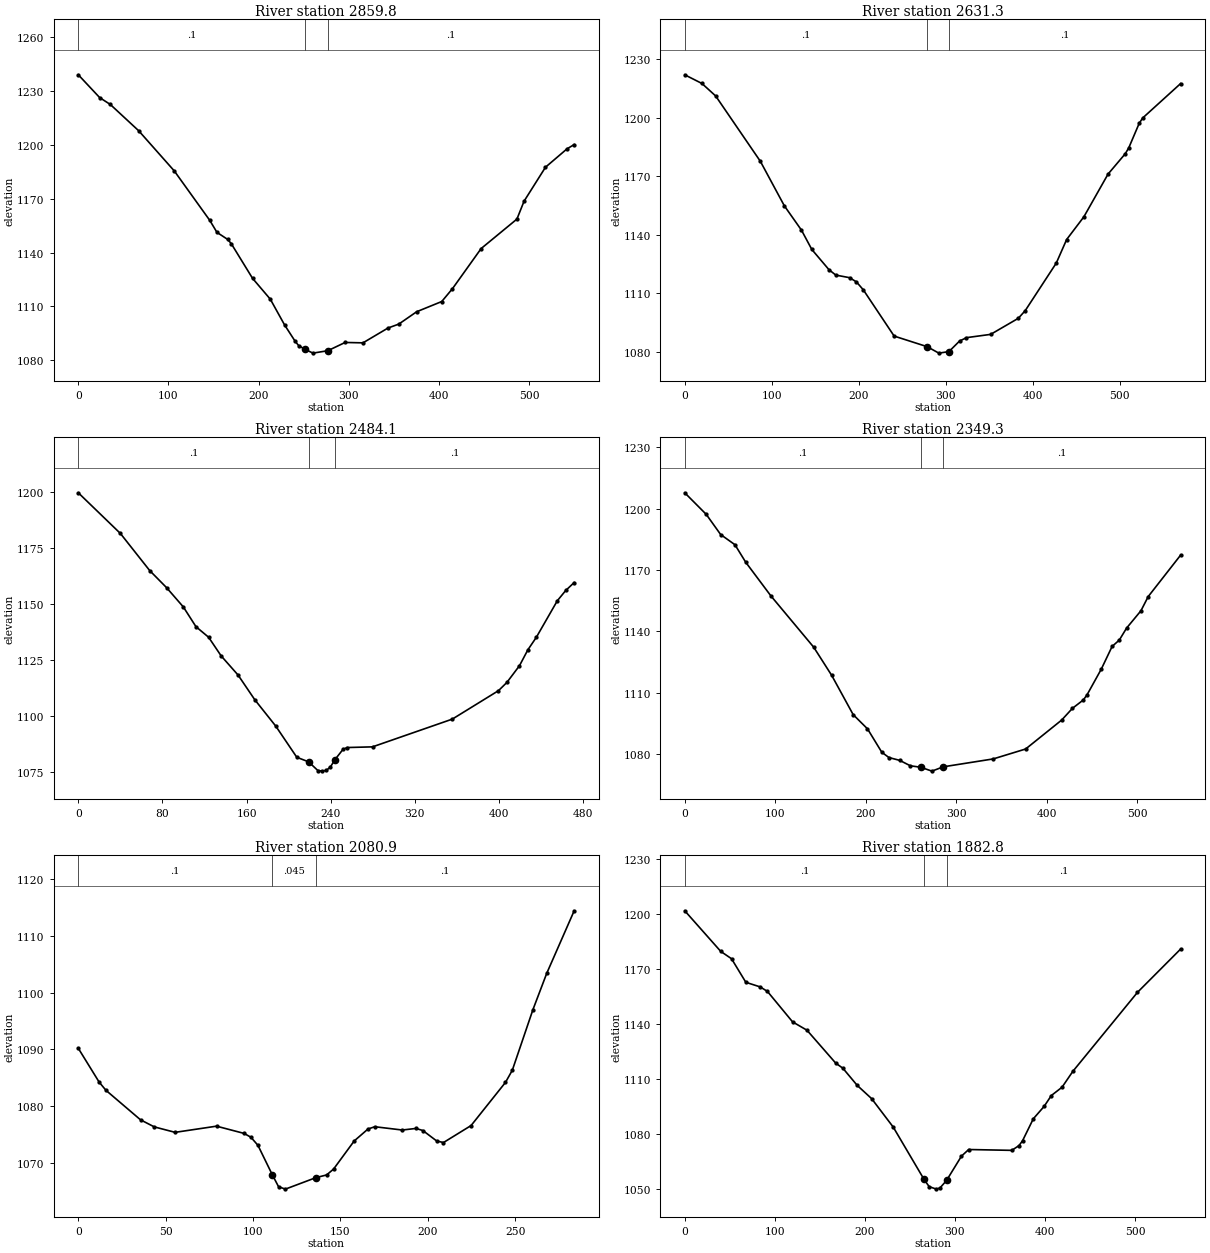
Type RM Length L Ch R = 1 ,2859.8,214.2,228.6,239.3
XS GIS Cut Line= 3
     1775294.405      320564.590     1775529.073      320426.747
     1775785.853      320320.402
#Sta/Elev= 30
       0 1239.12    23.7 1226.41    35.5 1222.58    67.0 1207.91   106.5 1185.50
   145.9 1157.90   153.8 1151.26   165.7 1147.33   169.6 1145.02   193.3 1125.62
   213.0 1113.99   228.8 1099.66   240.6 1090.48   244.6 1088.04   251.8 1085.99
   260.3 1083.92   276.8 1085.27   296.0 1089.87   315.8 1089.65   343.6 1097.93
   355.5 1100.10   375.4 1107.01   403.2 1112.70   415.1 1119.87   446.9 1142.24
   486.6 1158.67   494.5 1168.63   518.3 1187.60   542.2 1197.85   550.1 1200.22
#Mann= 3 , 0 , 0
       0     0.1       0   251.8   0.045       0   276.8     0.1       0
Bank Sta=251.8,276.8
Exp/Cntr=0.3,0.1

Type RM Length L Ch R = 1 ,2631.3,148,147.1,146.3
XS GIS Cut Line= 3
     1775310.613      320647.578     1775598.772      320641.128
     1775880.570      320629.468
#Sta/Elev= 30
       0 1221.95    19.7 1217.52    35.5 1211.12    86.9 1177.64   114.5 1154.83
   134.2 1142.36   146.1 1132.47   165.8 1122.12   173.7 1119.34   189.5 1118.02
   197.4 1115.86   205.3 1111.80   240.8 1088.09   278.8 1082.66   292.2 1079.36
   303.8 1080.14   316.0 1085.54   324.0 1087.29   351.8 1088.97   383.6 1097.20
   391.5 1101.09   427.3 1125.52   439.2 1137.57   459.0 1149.19   486.8 1171.08
   506.7 1181.56   510.7 1184.59   522.6 1197.04   526.6 1199.81   570.3 1217.48
#Mann= 3 , 0 , 0
       0     0.1       0   278.8   0.045       0   303.8     0.1       0
Bank Sta=278.8,303.8
Exp/Cntr=0.3,0.1

Type RM Length L Ch R = 1 ,2484.1,143.8,134.9,130
XS GIS Cut Line= 2
     1775360.925      320784.097     1775832.279      320769.774
#Sta/Elev= 30
       0 1199.67    40.0 1181.54    67.9 1164.97    83.9 1157.37    99.9 1148.73
   111.9 1139.93   123.9 1135.23   135.9 1126.87   151.9 1118.37   167.8 1107.36
   187.8 1095.56   207.8 1081.66     219 1079.63   227.8 1075.76   231.8 1075.48
   235.8 1075.80   239.8 1077.34     244 1080.57   251.8 1085.22   255.8 1086.01
   279.8 1086.31   355.7 1098.69   399.6 1111.38   407.6 1115.05   419.6 1122.53
   427.6 1129.64   435.6 1135.18   455.6 1151.52   463.6 1156.10   471.6 1159.63
#Mann= 3 , 0 , 0
       0     0.1       0     219   0.045       0     244     0.1       0
Bank Sta=219,244
Exp/Cntr=0.3,0.1

Type RM Length L Ch R = 1 ,2349.3,264.9,268.4,263.6
XS GIS Cut Line= 3
     1775337.818      320999.583     1775594.404      320906.383
     1775864.015      320853.752
#Sta/Elev= 30
       0 1207.81    23.7 1197.27    39.6 1187.42    55.4 1182.43    67.3 1173.87
    95.0 1157.47   142.4 1132.32   162.2 1118.59   186.0 1099.34   201.8 1092.40
   217.6 1080.96   225.5 1078.36   237.4 1076.98   249.2 1074.32   260.5 1073.63
   273.0 1071.72   285.5 1073.83   340.7 1077.69   376.5 1082.54   416.3 1096.69
   428.2 1102.43   440.2 1106.52   444.2 1108.93   460.1 1121.63   472.0 1132.68
   480.0 1135.83   488.0 1141.66   503.9 1150.16   511.9 1157.09   547.7 1177.35
#Mann= 3 , 0 , 0
       0     0.1       0   260.5   0.045       0   285.5     0.1       0
Bank Sta=260.5,285.5
Exp/Cntr=0.3,0.1

Type RM Length L Ch R = 1 ,2080.9,196.2,198.1,203.6
XS GIS Cut Line= 3
     1775570.083      321112.916     1775652.114      321168.038
     1775825.291      321102.934
#Sta/Elev= 30
       0 1090.18    11.9 1084.23    15.8 1082.78    35.6 1077.57    43.5 1076.32
    55.4 1075.36    79.1 1076.45    94.9 1075.17    98.8 1074.49   102.8 1073.07
     111 1067.89   114.6 1065.77   118.5 1065.34     136 1067.37   142.1 1067.84
   146.1 1068.88   157.9 1073.84   165.8 1075.95   169.7 1076.35   185.4 1075.77
   193.3 1076.05   197.2 1075.68   205.1 1073.84   209.0 1073.56   224.8 1076.56
   244.5 1084.18   248.4 1086.32   260.2 1097.01   268.1 1103.42   283.8 1114.45
#Mann= 3 , 0 , 0
       0     0.1       0     111   0.045       0     136     0.1       0
Bank Sta=111,136
Exp/Cntr=0.3,0.1

Type RM Length L Ch R = 1 ,1882.8,326.4,321.2,315.7
XS GIS Cut Line= 2
     1775448.851      321393.803     1775992.594      321306.303
#Sta/Elev= 30
       0 1201.50    39.9 1179.40    51.9 1175.39    67.8 1162.54    83.8 1160.02
    91.8 1157.56   119.7 1140.98   135.7 1136.42   167.6 1118.50   175.6 1115.69
   191.6 1106.30   207.5 1099.14   231.5 1083.62   265.7 1055.14   271.4 1051.17
   279.4 1049.81   283.4 1050.44   290.7 1054.52   307.3 1067.80   315.3 1071.40
   363.2 1070.94   371.2 1073.55   375.1 1076.15   387.1 1088.16   399.1 1094.91
   407.1 1100.82   419.0 1105.36   431.0 1114.01   502.8 1157.08   550.7 1180.66
#Mann= 3 , 0 , 0
       0     0.1       0   265.7   0.045       0   290.7     0.1       0
Bank Sta=265.7,290.7
Exp/Cntr=0.3,0.1

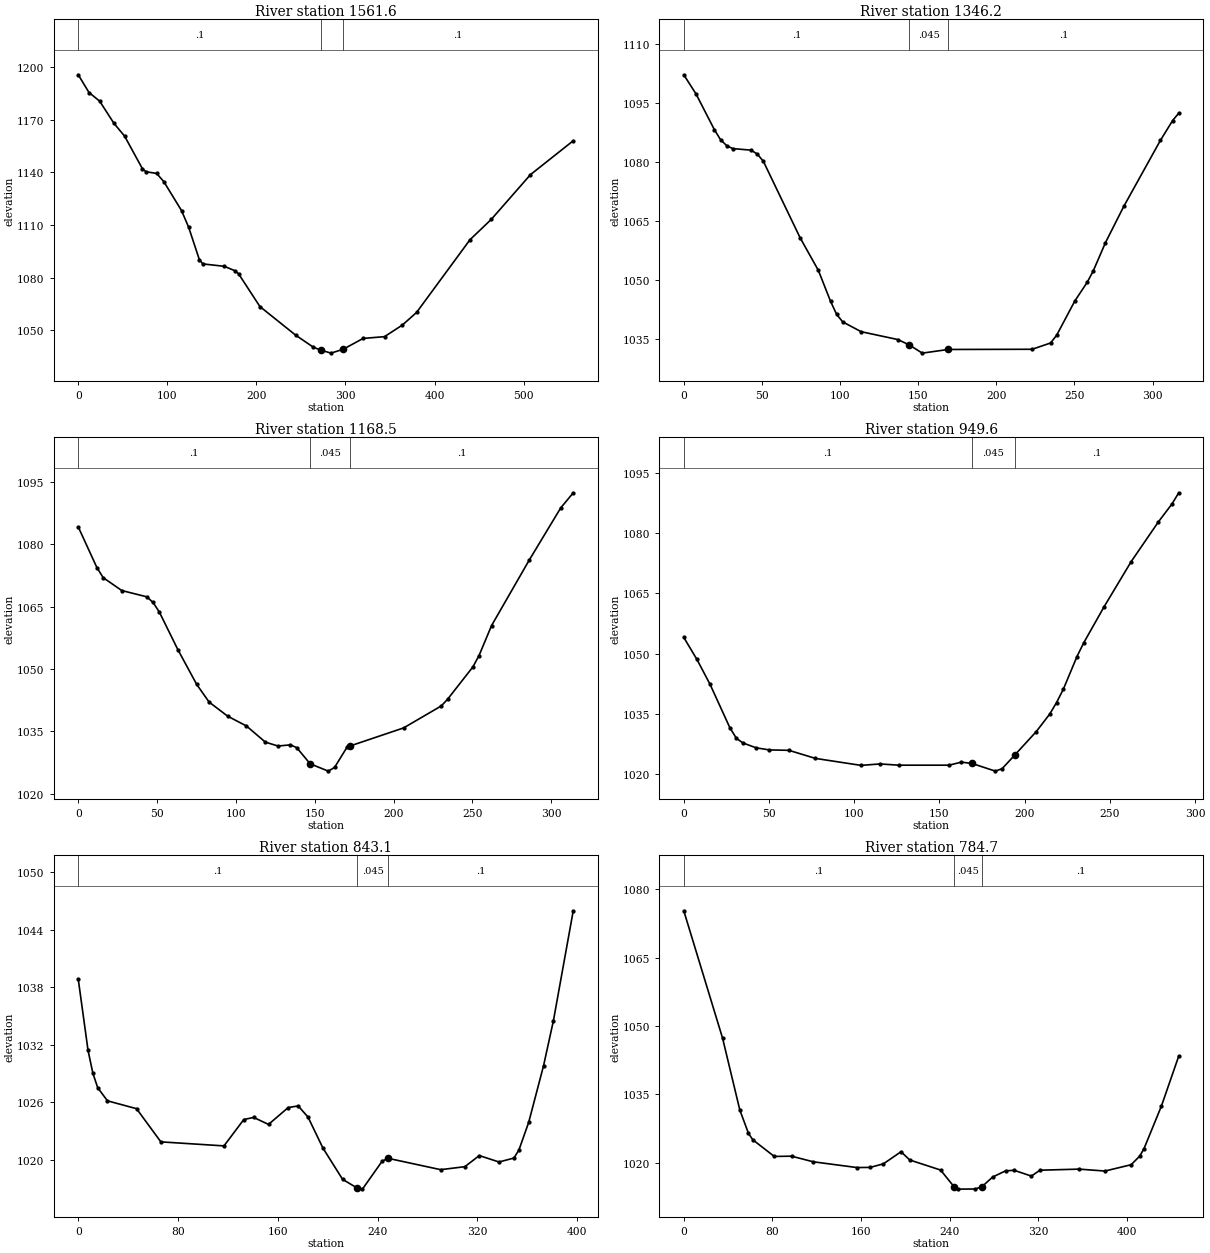
Type RM Length L Ch R = 1 ,1561.6,219.2,215.4,213.5
XS GIS Cut Line= 2
     1775474.103      321741.257     1775995.924      321550.165
#Sta/Elev= 30
       0 1195.70    12.0 1185.61    24.0 1180.67    40.0 1168.04    52.0 1160.71
    72.0 1142.09    76.0 1140.39    88.0 1139.40    96.0 1134.75   115.9 1118.22
   123.9 1108.72   135.9 1090.24   139.9 1087.76   163.9 1086.40   175.9 1083.86
   179.9 1082.17   203.9 1063.44   243.9 1047.15   263.9 1040.23   272.4 1038.54
   283.8 1036.84   297.4 1039.05   319.8 1045.23   343.8 1046.24   363.8 1052.84
   379.8 1060.06   439.8 1101.58   463.8 1113.25   507.7 1138.73   555.7 1158.06
#Mann= 3 , 0 , 0
       0     0.1       0   272.4   0.045       0   297.4     0.1       0
Bank Sta=272.4,297.4
Exp/Cntr=0.3,0.1

Type RM Length L Ch R = 1 ,1346.2,163.5,177.8,188.4
XS GIS Cut Line= 3
     1775647.079      321917.439     1775786.663      321846.606
     1775935.274      321786.883
#Sta/Elev= 30
       0 1102.14     7.8 1097.30    19.6 1088.18    23.5 1085.66    27.4 1084.16
    31.3 1083.38    43.0 1082.99    47.0 1082.01    50.9 1080.16    74.4 1060.73
    86.1 1052.42    93.9 1044.56    97.8 1041.23   101.7 1039.31   113.5 1036.82
   137.0 1034.82   144.2 1033.47   152.6 1031.37   169.2 1032.30   222.9 1032.35
   234.7 1033.95   238.6 1035.93   250.3 1044.69   258.1 1049.36   262.0 1052.27
   269.8 1059.45   281.5 1068.66   305.0 1085.49   312.8 1090.51   316.7 1092.39
#Mann= 3 , 0 , 0
       0     0.1       0   144.2   0.045       0   169.2     0.1       0
Bank Sta=144.2,169.2
Exp/Cntr=0.3,0.1

Type RM Length L Ch R = 1 ,1168.5,187.2,218.9,219.1
XS GIS Cut Line= 3
     1775696.385      321992.439     1775793.607      321975.078
     1776008.885      321972.474
#Sta/Elev= 30
       0 1084.11    11.8 1074.37    15.8 1071.94    27.6 1068.85    43.4 1067.35
    47.4 1066.02    51.4 1063.70    63.2 1054.64    75.1 1046.32    83.0 1042.06
    94.8 1038.67   106.7 1036.32   118.7 1032.44   126.7 1031.51   134.6 1031.79
   138.6 1031.11   147.1 1027.24   158.6 1025.48   162.6 1026.37   170.5 1031.24
   172.1 1031.48   206.4 1035.86   230.3 1041.14   234.3 1042.75   250.3 1050.49
   254.2 1053.20   262.2 1060.45   286.2 1076.24   306.1 1088.72   314.0 1092.32
#Mann= 3 , 0 , 0
       0     0.1       0   147.1   0.045       0   172.1     0.1       0
Bank Sta=147.1,172.1
Exp/Cntr=0.3,0.1

Type RM Length L Ch R = 1 ,949.6,17.4,106.6,147.2
XS GIS Cut Line= 5
     1775758.150      322090.442     1775846.777      322137.393
     1775878.027      322157.359     1775887.142      322181.230
     1776014.636      322181.956
#Sta/Elev= 30
       0 1054.00     7.7 1048.54    15.4 1042.34    27.0 1031.56    30.9 1028.87
    34.7 1027.74    42.4 1026.53    50.2 1026.00    61.7 1025.90    77.2 1023.89
   104.0 1022.15   115.1 1022.51   126.2 1022.20   155.6 1022.20   162.9 1022.96
   169.1 1022.63   182.8 1020.72   186.8 1021.34   194.1 1024.68   206.8 1030.56
   214.7 1034.92   218.7 1037.78   222.7 1041.12   230.7 1049.25   234.6 1052.62
   246.6 1061.64   262.5 1072.89   278.5 1082.80   286.4 1087.22   290.4 1090.01
#Mann= 3 , 0 , 0
       0     0.1       0   169.1   0.045       0   194.1     0.1       0
Bank Sta=169.1,194.1
Exp/Cntr=0.3,0.1

Type RM Length L Ch R = 1 ,843.1,141.3,58.3,58.9
XS GIS Cut Line= 6
     1775770.091      322125.798     1775874.258      322169.201
     1775891.619      322234.305     1775915.230      322305.833
     1775925.473      322374.930     1775995.786      322387.083
#Sta/Elev= 30
       0 1038.82     7.8 1031.44    11.7 1029.03    15.6 1027.52    23.4 1026.16
    46.7 1025.34    66.2 1021.88   116.8 1021.46   132.7 1024.21   140.6 1024.43
   152.5 1023.70   168.3 1025.46   176.3 1025.63   184.2 1024.46   196.1 1021.24
   211.9 1017.97   223.5 1017.07   227.8 1016.95   243.7 1019.88   248.5 1020.16
   290.5 1018.98   309.9 1019.29   321.5 1020.45   337.3 1019.78   349.2 1020.19
   353.2 1021.01   361.1 1023.92   373.0 1029.82   380.9 1034.51   396.8 1045.98
#Mann= 3 , 0 , 0
       0     0.1       0   223.5   0.045       0   248.5     0.1       0
Bank Sta=223.5,248.5
Exp/Cntr=0.3,0.1

Type RM Length L Ch R = 1 ,784.7,176.9,144.1,105.1
XS GIS Cut Line= 6
     1775727.383      322151.319     1775831.550      322194.722
     1775848.911      322259.826     1775872.522      322331.354
     1775882.765      322400.451     1776001.689      322425.104
#Sta/Elev= 30
       0 1075.29    35.0 1047.36    50.6 1031.58    58.4 1026.46    62.3 1025.06
    81.7 1021.40    97.3 1021.46   116.8 1020.23   156.4 1018.96   168.3 1019.00
   180.2 1019.78   196.1 1022.43   204.0 1020.62   231.8 1018.42   244.3 1014.66
   247.6 1014.23   263.3 1014.26   269.3 1014.80   278.8 1016.88   290.5 1018.24
   298.2 1018.36   313.8 1017.09   321.5 1018.38   356.8 1018.62   380.2 1018.20
   403.8 1019.58   411.6 1021.47   415.5 1023.14   431.2 1032.47   446.8 1043.41
#Mann= 3 , 0 , 0
       0     0.1       0   244.3   0.045       0   269.3     0.1       0
Bank Sta=244.3,269.3
Exp/Cntr=0.3,0.1

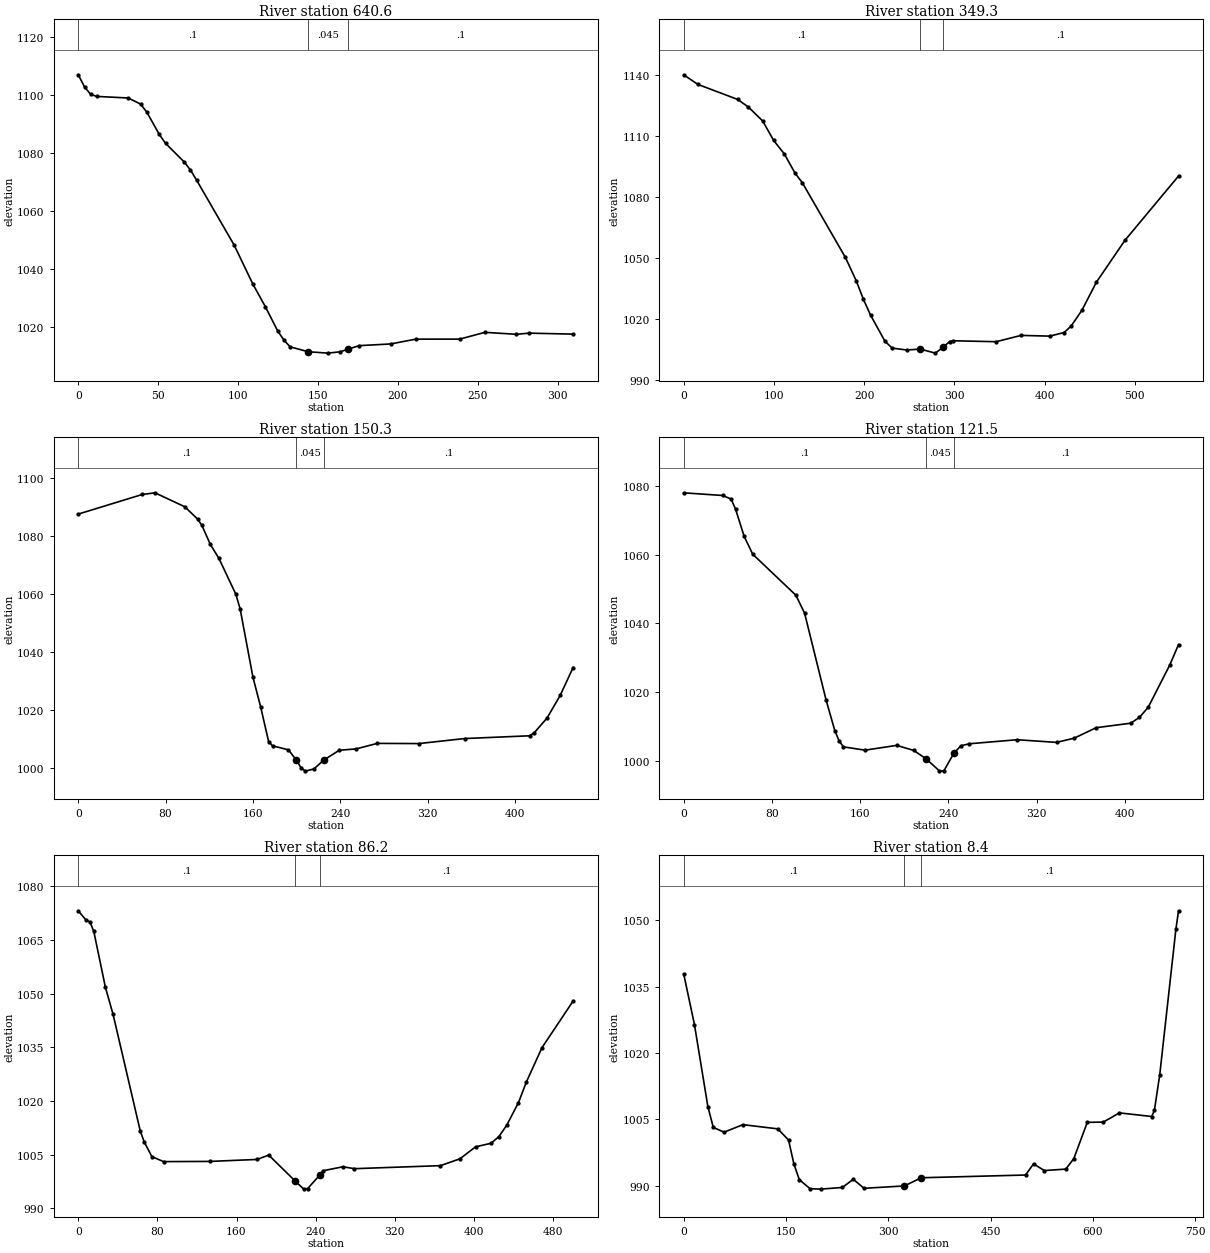
Type RM Length L Ch R = 1 ,640.6,306.6,291.4,275
XS GIS Cut Line= 3
     1775650.300      322427.882     1775801.341      322446.111
     1775958.459      322455.660
#Sta/Elev= 30
       0 1107.09     3.9 1102.93     7.8 1100.30    11.7 1099.62    31.2 1099.08
    39.0 1096.97    42.9 1094.15    50.7 1086.47    54.6 1083.40    66.3 1076.94
    70.2 1074.16    74.1 1070.60    97.5 1048.23   109.2 1034.76   117.0 1026.95
   124.8 1018.47   128.7 1015.33   132.6 1013.01   143.9 1011.33   156.1 1010.85
   163.9 1011.31   168.9 1012.25   175.8 1013.44   195.4 1014.02   211.2 1015.69
   238.7 1015.70   254.4 1018.04   274.1 1017.36   282.0 1017.76   309.6 1017.42
#Mann= 3 , 0 , 0
       0     0.1       0   143.9   0.045       0   168.9     0.1       0
Bank Sta=143.9,168.9
Exp/Cntr=0.3,0.1

Type RM Length L Ch R = 1 ,349.3,226.6,198.9,171
XS GIS Cut Line= 3
     1775673.634      322817.794     1775926.271      322709.667
     1776166.551      322578.994
#Sta/Elev= 30
       0 1139.98    15.9 1135.24    59.7 1127.90    71.7 1124.14    87.6 1117.26
    99.6 1107.77   111.5 1101.10   123.5 1091.54   131.4 1086.97   179.2 1050.16
   191.2 1038.69   199.1 1029.62   207.1 1021.76   223.0 1008.96   231.0 1005.58
   246.9 1004.64   262.3 1005.08   278.8 1003.10   287.3 1005.91   294.6 1008.74
   298.6 1009.18   346.2 1008.72   373.9 1011.82   405.6 1011.46   421.5 1013.23
   429.4 1016.44   441.3 1024.22   457.2 1037.91   488.9 1058.56   548.3 1090.20
#Mann= 3 , 0 , 0
       0     0.1       0   262.3   0.045       0   287.3     0.1       0
Bank Sta=262.3,287.3
Exp/Cntr=0.3,0.1

Type RM Length L Ch R = 1 ,150.3,31.2,28.8,29.2
XS GIS Cut Line= 6
     1775884.855      322984.856     1776022.659      322903.476
     1776038.197      322879.301     1776045.489      322794.405
     1776036.635      322718.884     1776110.419      322646.488
#Sta/Elev= 30
       0 1087.63    58.6 1094.40    70.3 1094.97    97.6 1090.16   109.3 1085.91
   113.2 1083.78   121.0 1077.16   128.8 1072.38   144.4 1059.93   148.3 1054.89
   160.0 1031.37   167.2 1020.89   174.4 1009.08   178.0 1007.62   192.6 1006.24
   199.7 1002.75   204.3  999.96   208.1  998.89   215.9  999.65   224.7 1002.64
   239.1 1006.09   254.6 1006.57   274.0 1008.47   312.0 1008.40   354.0 1010.14
   413.6 1011.09   417.6 1012.07   429.5 1017.22   441.5 1025.01   453.4 1034.66
#Mann= 3 , 0 , 0
       0     0.1       0   199.7   0.045       0   224.7     0.1       0
Bank Sta=199.7,224.7
Exp/Cntr=0.3,0.1

Type RM Length L Ch R = 1 ,121.5,16.9,35.4,53.6
XS GIS Cut Line= 6
     1775902.086      322995.099     1776049.742      322922.920
     1776065.280      322898.745     1776072.572      322813.849
     1776079.864      322730.516     1776137.503      322665.933
#Sta/Elev= 30
       0 1077.98    35.2 1077.21    43.0 1076.18    47.0 1073.25    54.8 1065.33
    62.6 1060.12   101.7 1048.20   109.6 1042.97   129.1 1017.70   137.0 1008.79
   140.9 1005.83   144.8 1004.09   164.4 1003.14   193.1 1004.53   208.6 1003.05
   219.8 1000.59   231.8  997.10   235.7  997.04   244.8 1002.20   251.2 1004.40
   258.9 1005.00   302.2 1006.17   338.0 1005.40   354.0 1006.63   373.8 1009.67
   405.2 1010.98   413.1 1012.68   421.0 1015.60   440.6 1027.91   448.5 1033.84
#Mann= 3 , 0 , 0
       0     0.1       0   219.8   0.045       0   244.8     0.1       0
Bank Sta=219.8,244.8
Exp/Cntr=0.3,0.1

Type RM Length L Ch R = 1 ,86.2,78.1,77.8,76.9
XS GIS Cut Line= 4
     1775912.503      322997.183     1776004.864      322979.821
     1776129.864      322843.016     1776306.253      322709.683
#Sta/Elev= 30
       0 1073.14     7.8 1070.56    11.8 1070.01    15.7 1067.38    27.4 1051.79
    35.2 1044.16    62.6 1011.68    66.6 1008.55    74.4 1004.43    86.2 1003.02
   133.4 1003.08   180.7 1003.63   192.6 1004.84   219.1  997.65   228.0  995.33
   232.0  995.49   244.1  999.24   247.8 1000.48   267.5 1001.58   279.3 1001.05
   366.2 1001.89   385.9 1003.80   401.7 1007.15   417.5 1008.16   425.4 1010.04
   433.3 1013.22   445.1 1019.50   453.0 1025.20   468.8 1034.84   500.4 1047.93
#Mann= 3 , 0 , 0
       0     0.1       0   219.1   0.045       0   244.1     0.1       0
Bank Sta=219.1,244.1
Exp/Cntr=0.3,0.1

Type RM Length L Ch R = 1 ,8.4,0.1,8.4,17.1
XS GIS Cut Line= 5
     1775854.864      323071.488     1776039.586      323056.210
     1776160.419      322920.099     1776329.169      322811.071
     1776411.808      322677.044
#Sta/Elev= 30
       0 1037.87    15.8 1026.40    35.5 1007.84    43.4 1003.16    59.2 1002.06
    86.8 1003.77   138.0 1002.82   153.8 1000.29   161.7  994.85   169.6  991.33
   185.4  989.28   201.2  989.19   232.8  989.57   248.7  991.42   264.5  989.38
   323.5  989.91   348.5  991.76   501.3  992.38   513.1  994.90   528.9  993.39
   560.4  993.72   572.2  996.11   591.9 1004.29   615.5 1004.35   639.1 1006.43
   686.4 1005.61   690.3 1006.98   698.2 1015.10   721.8 1047.90   725.7 1052.12
#Mann= 3 , 0 , 0
       0     0.1       0   323.5   0.045       0   348.5     0.1       0
Bank Sta=323.5,348.5
Exp/Cntr=0.3,0.1